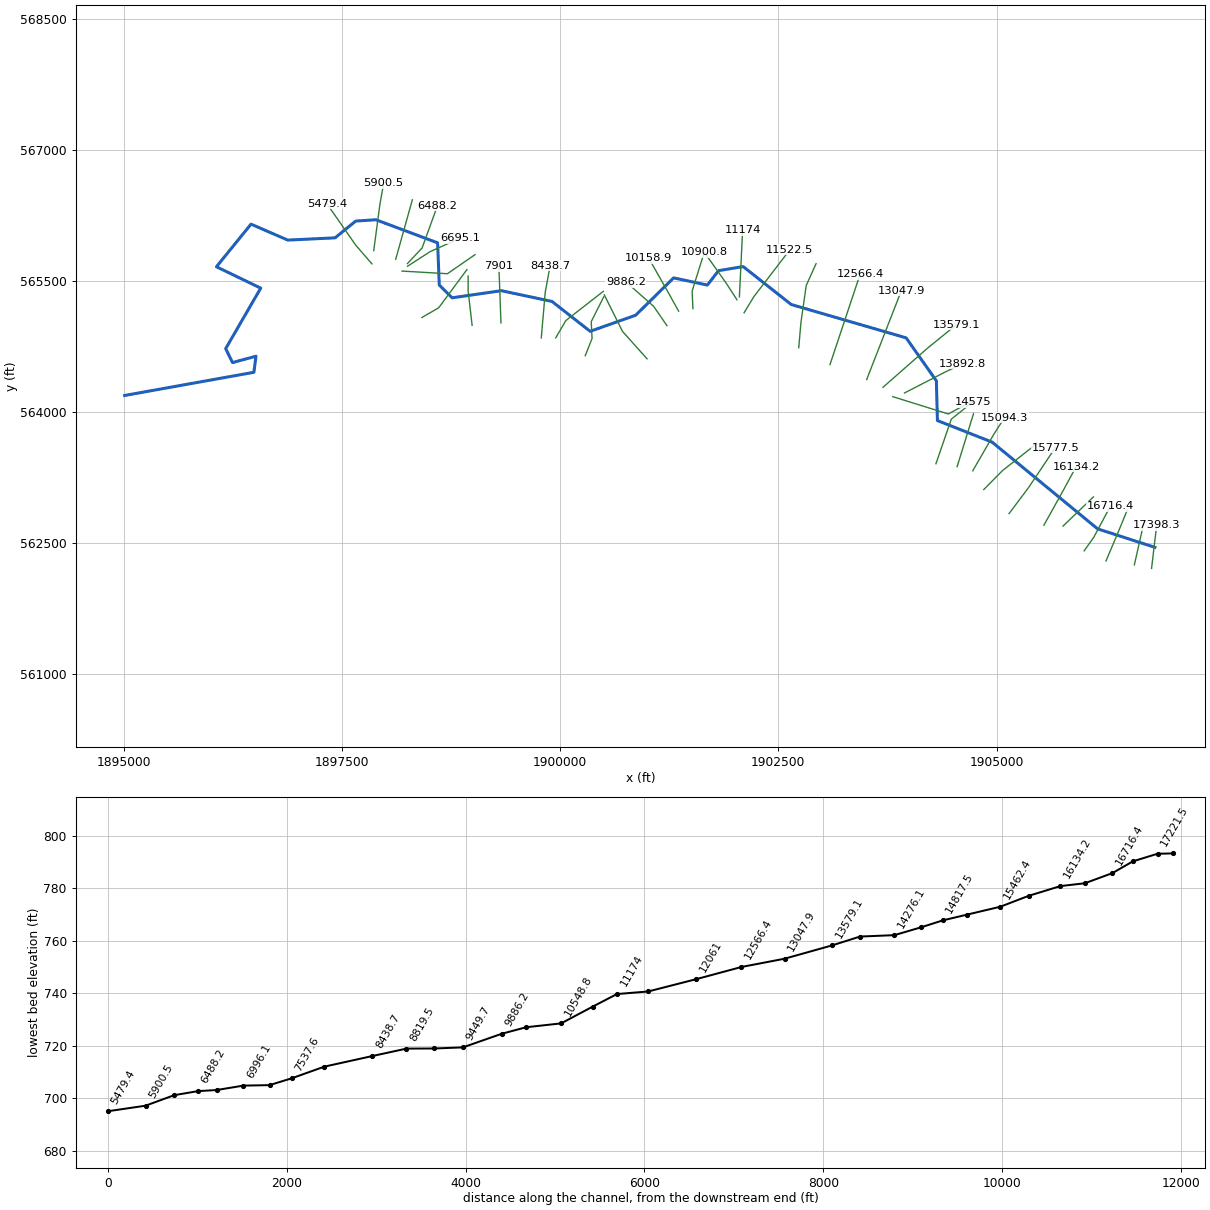
--- PigeonRun.prj (project) ---

Proj Title=PigeonRun
Current Plan=p01
Default Exp/Contr=0,0
English Units
Geom File=g01
Flow File=f01
Plan File=p01
BEGIN DESCRIPTION:
AMEC Environment & Infrastructure, 2013
Projection: NAD 1983 State Plane West Virginia South FIPS 4702 (US Feet)
Vertical Datum: NAVD 1988
END DESCRIPTION:
DSS Export Rating Curves= 0
DSS Export Rating Curve Sorted= 0
DSS Export Volume Flow Curves= 0
DXF OffsetX= 0
DXF OffsetY= 0
DXF ScaleX= 0
DXF ScaleY= 0

--- PigeonRun.p01 (plan) ---

Plan Title=Floodplain
Program Version=4.00
Geom File=g01
Flow File=f01
K Sum by GR=0
Std Step Tol=0.01
Critical Tol=0.01
Num of Std Step Trials=20
Max Error Tol=0.3
Flow Tol Ratio=0.001
Split Flow NTrial=30
Split Flow Tol=0.02
Split Flow Ratio=0.02
Log Output Level=0
Friction Slope Method=1
Unsteady Friction Slope Method=2
Unsteady Bridges Friction Slope Method=1
Global Log Level=0
CheckData=False
Run HTab=0
Run UNet=0
Run PostProcess=0
UNET Theta=0
UNET Theta Warmup=0
UNET ZTol=0
UNET ZSATol=0
UNET MxIter=0
UNET MaxInSteps=0
UNET DtIC=0
UNET DtMin=0
UNET MaxCRTS=0
UNET WFStab=0
UNET SFStab=0
UNET WFX=0
UNET SFX=0
UNET DSS MLevel=0
UNET DZMax Abort=0
UNET Convert EG Bridges=0
UNET Use Existing IB Tables=0
UNET Froude Limit=0
UNET Froude Power=0
Write IC File=0
Echo Input=False
Echo Output=False
Write Detailed=0

--- PigeonRun.f01 (steady flow) ---

Flow Title=NFF Regression Equation
Program Version=4.10
Number of Profiles= 1
Profile Names=P100yr
River Rch & RM=PigeonRun,Main            ,17398.3
896.9355
River Rch & RM=PigeonRun,Main            ,15777.5
975.8709
River Rch & RM=PigeonRun,Main            ,14276.1
1081.467
River Rch & RM=PigeonRun,Main            ,13047.9
1134.418
River Rch & RM=PigeonRun,Main            ,9128.6
1254.561
River Rch & RM=PigeonRun,Main            ,1736.8
1372.674
River Rch & RM=PigeonRun,Main            ,1226.9
1553.337
River Rch & RM=PigeonRun,Main            ,425.8
1556.513
Boundary for River Rch & Prof#=PigeonRun,Main            , 1
Up Type= 0
Dn Type= 3
Dn Slope=0.00753
DSS Import GetInterval= 0
DSS Import GetPeak= 0
DSS Import FillOption= 0

--- PigeonRun.g01 (geometry) ---

Geom Title=USGS 3m DEM
Program Version=4.10

River Reach=PigeonRun       ,Main
Reach XY= 30
       1906812.5      562452.004     1906156.022       562663.87
     1904948.581      563656.827      1904322.04      563903.841
     1904309.874      564358.857     1903963.899      564850.876
     1902647.501      565232.972     1902096.873      565667.671
     1901815.528      565620.774     1901687.015      565455.785
      1901300.57      565538.009     1900865.562      565110.164
     1900344.555      564926.062     1899907.404      565268.303
     1899327.661      565391.286     1898764.147       565309.84
     1898616.524       565455.72     1898597.549      565939.587
     1897889.658      566203.925     1897658.677       566188.29
     1897422.692      565996.654     1896881.454      565970.832
     1896460.353      566153.529     1896064.396      565665.507
     1896571.518      565420.643     1896170.355       564727.69
      1896248.51      564567.915     1896517.698      564640.863
     1896493.388      564456.772     1895012.763      564191.172

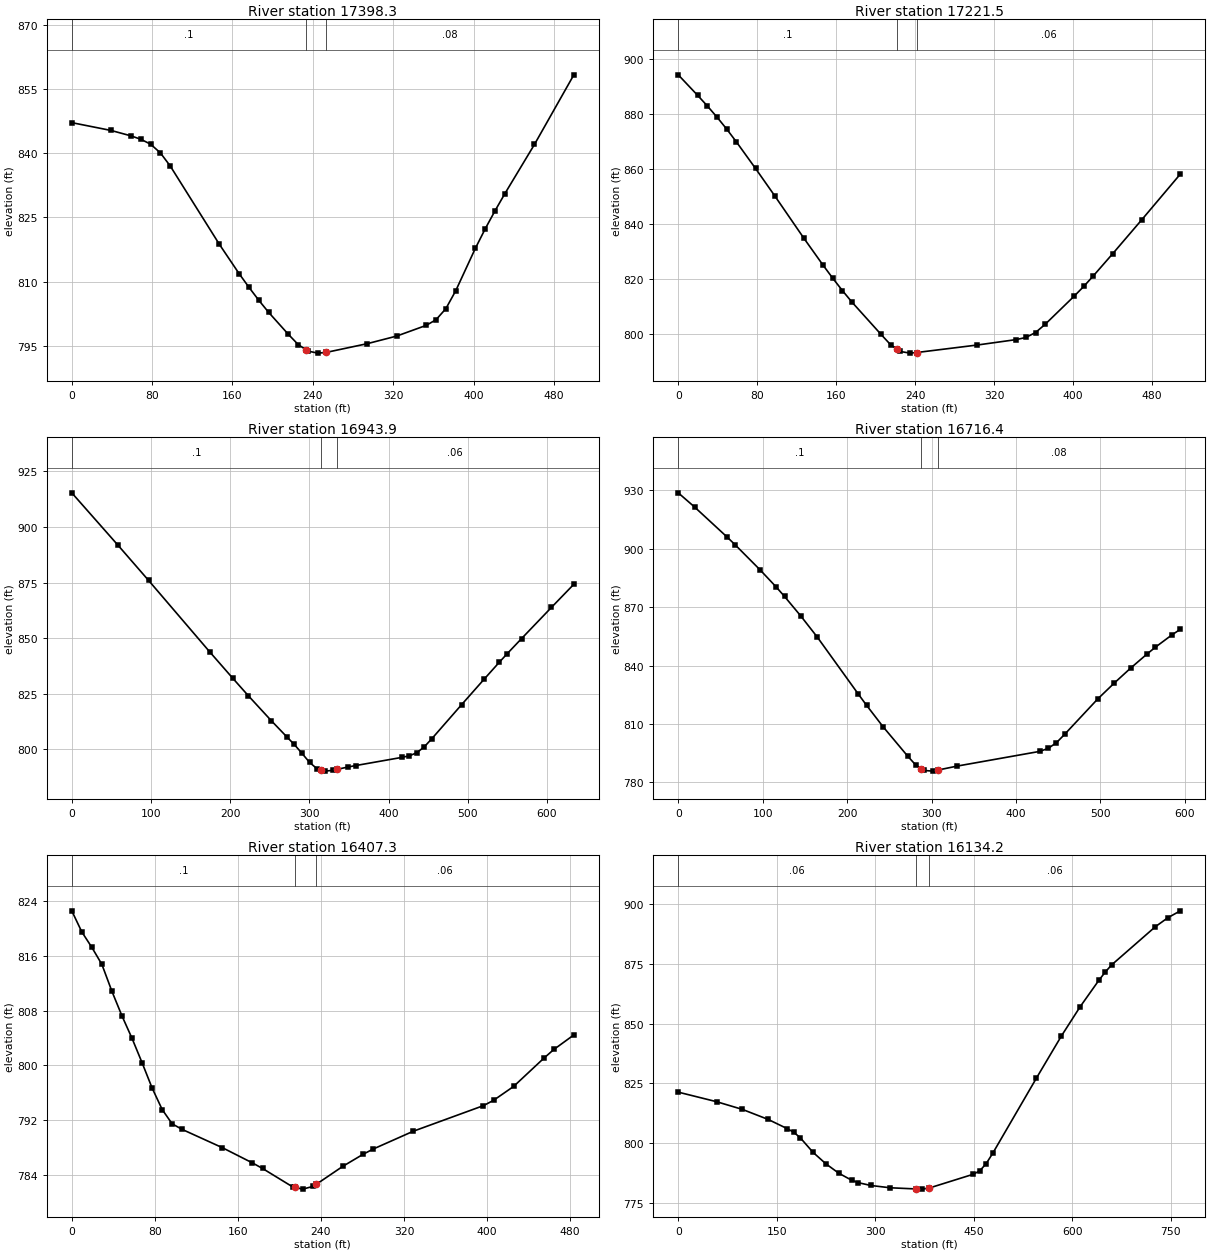
Type RM Length L Ch R = 1 ,17398.3 ,179.4,176.8,174.2
XS GIS Cut Line= 2
     1906774.549      562211.137     1906833.482      562707.416
#Sta/Elev= 30
       0  847.12    39.2  845.29    58.8  844.04    68.6  843.25    78.4   842.1
    88.2  840.06      98     837     147  818.67   166.6  811.84   176.4  808.65
   186.2  805.62     196   802.8   215.6  797.67   225.4  795.28   232.9  794.11
   235.2  793.75     245  793.28   252.9  793.43     294  795.48   323.4  797.26
   352.8  799.76   362.6  801.08   372.4  803.67   382.2  807.84   401.8  817.78
   411.6  822.33   421.4  826.56   431.2  830.56   460.6  842.03   499.8  858.29
#Mann= 3 , 0 , 0
       0      .1       0   232.9    .045       0   252.9     .08       0
Bank Sta=232.9,252.9
XS Rating Curve= 0 ,0
Exp/Cntr=0.3,0.1

Type RM Length L Ch R = 1 ,17221.5 ,282.1,277.6,273.1
XS GIS Cut Line= 2
     1906577.588       562251.46     1906689.251      562747.738
#Sta/Elev= 30
       0  894.38    19.6  886.94    29.4  883.09    39.1  879.07    48.9  874.74
    58.7   870.1    78.3  860.33    97.8  850.36   127.2     835   146.7  825.17
   156.5  820.43   166.3  815.92   176.1  811.68   205.4     800   215.2   796.2
   221.6  794.61     225  793.76   234.8  793.16   241.6  793.38   303.2  796.12
   342.4  798.08   352.2  798.85     362  800.65   371.7  803.62   401.1  813.86
   410.9  817.43   420.6  821.27   440.2  829.32   469.6  841.65   508.7  858.27
#Mann= 3 , 0 , 0
       0      .1       0   221.6    .045       0   241.6     .06       0
Bank Sta=221.6,241.6
XS Rating Curve= 0 ,0
Exp/Cntr=0.3,0.1

Type RM Length L Ch R = 1 ,16943.9 ,229.8,227.5,225.2
XS GIS Cut Line= 3
     1906252.875      562295.854     1906418.301      562688.741
     1906496.879      562881.049
#Sta/Elev= 30
       0  915.32    58.1  891.88    96.9  875.99   174.4  843.76   203.5  831.91
   222.8  824.19   251.9  812.94   271.3  805.74     281  802.22   290.6  798.28
   300.3  794.17     310  791.22   314.4  790.78   319.7  790.25   329.4   790.6
   334.4     791   348.8   792.1   358.5  792.75   416.6  796.41   426.3  797.13
   435.7  798.52   445.2  801.19   454.6  804.79   492.4  820.17   520.7  831.56
   539.6  839.08     549  842.71   567.9  849.79   605.7  863.82     634  874.23
#Mann= 3 , 0 , 0
       0      .1       0   314.4    .045       0   334.4     .06       0
Bank Sta=314.4,334.4
XS Rating Curve= 0 ,0
Exp/Cntr=0.3,0.1

Type RM Length L Ch R = 1 ,16716.4 ,317,309.1,301.2
XS GIS Cut Line= 3
     1906002.216        562411.2     1906113.878      562569.388
     1906303.084      562922.987
#Sta/Elev= 30
       0  928.78    19.4  921.47    58.1  905.97    67.8  901.91    96.8  889.26
   116.2  880.32   125.9  875.53   145.2  865.48   164.6  854.71   213.2  825.42
     223  819.64   242.5  808.65   271.9  793.42   281.7  788.74   287.7  787.13
   291.4  786.13   301.2  785.78   307.7  786.34   330.6  788.39   428.4  795.94
   438.2  797.47     448   800.4   457.7  804.69   496.8  822.83   516.4     831
     536  838.77   555.5  846.04   565.3  849.49   584.9  855.83   594.7  858.63
#Mann= 3 , 0 , 0
       0      .1       0   287.7    .045       0   307.7     .08       0
Bank Sta=287.7,307.7
XS Rating Curve= 0 ,0
Exp/Cntr=0.3,0.1

Type RM Length L Ch R = 1 ,16407.3 ,265.5,273.1,280.6
XS GIS Cut Line= 2
      1905760.28      562695.009     1906109.226      563029.997
#Sta/Elev= 30
       0   822.6     9.7  819.51    19.4  817.24      29  814.77    38.7  810.82
    48.4  807.22      58  803.97    67.7   800.4    77.4  796.69    87.1  793.54
    96.7  791.45   106.4  790.63   145.1  787.96   174.1  785.73   183.8  784.92
   212.8  782.23   215.4  782.14   222.5   781.9   232.2  782.29   235.4  782.59
   261.2  785.24   280.6  786.99   290.2  787.75   328.9  790.36   396.6  794.11
   406.3  794.88   425.7  796.92   454.7  801.03   464.4  802.32   483.7  804.45
#Mann= 3 , 0 , 0
       0      .1       0   215.4    .045       0   235.4     .06       0
Bank Sta=215.4,235.4
XS Rating Curve= 0 ,0
Exp/Cntr=0.3,0.1

Type RM Length L Ch R = 1 ,16134.2 ,358.7,356.6,354.5
XS GIS Cut Line= 3
     1905541.607      562705.865     1905774.238        563124.6
     1905910.714      563375.841
#Sta/Elev= 30
       0  821.37    58.6  817.36    97.8  814.15   136.9  809.97   166.2  806.09
     176  804.59   185.7  802.36   205.3  796.22   224.8  791.44   244.4  787.51
     264  784.57   273.7  783.56   293.3  782.35   322.6  781.39   361.9   780.9
   371.5  780.82   381.9  781.24   449.7  787.06   459.5   788.5   469.2  791.51
     479  795.75   545.7  827.24   583.8  844.88   612.4  857.12     641   868.2
   650.6  871.59   660.1  874.53   726.8  890.52   745.9  894.29   764.9  897.18
#Mann= 3 , 0 , 0
       0     .06       0   361.9    .045       0   381.9     .06       0
Bank Sta=361.9,381.9
XS Rating Curve= 0 ,0
Exp/Cntr=0.3,0.1

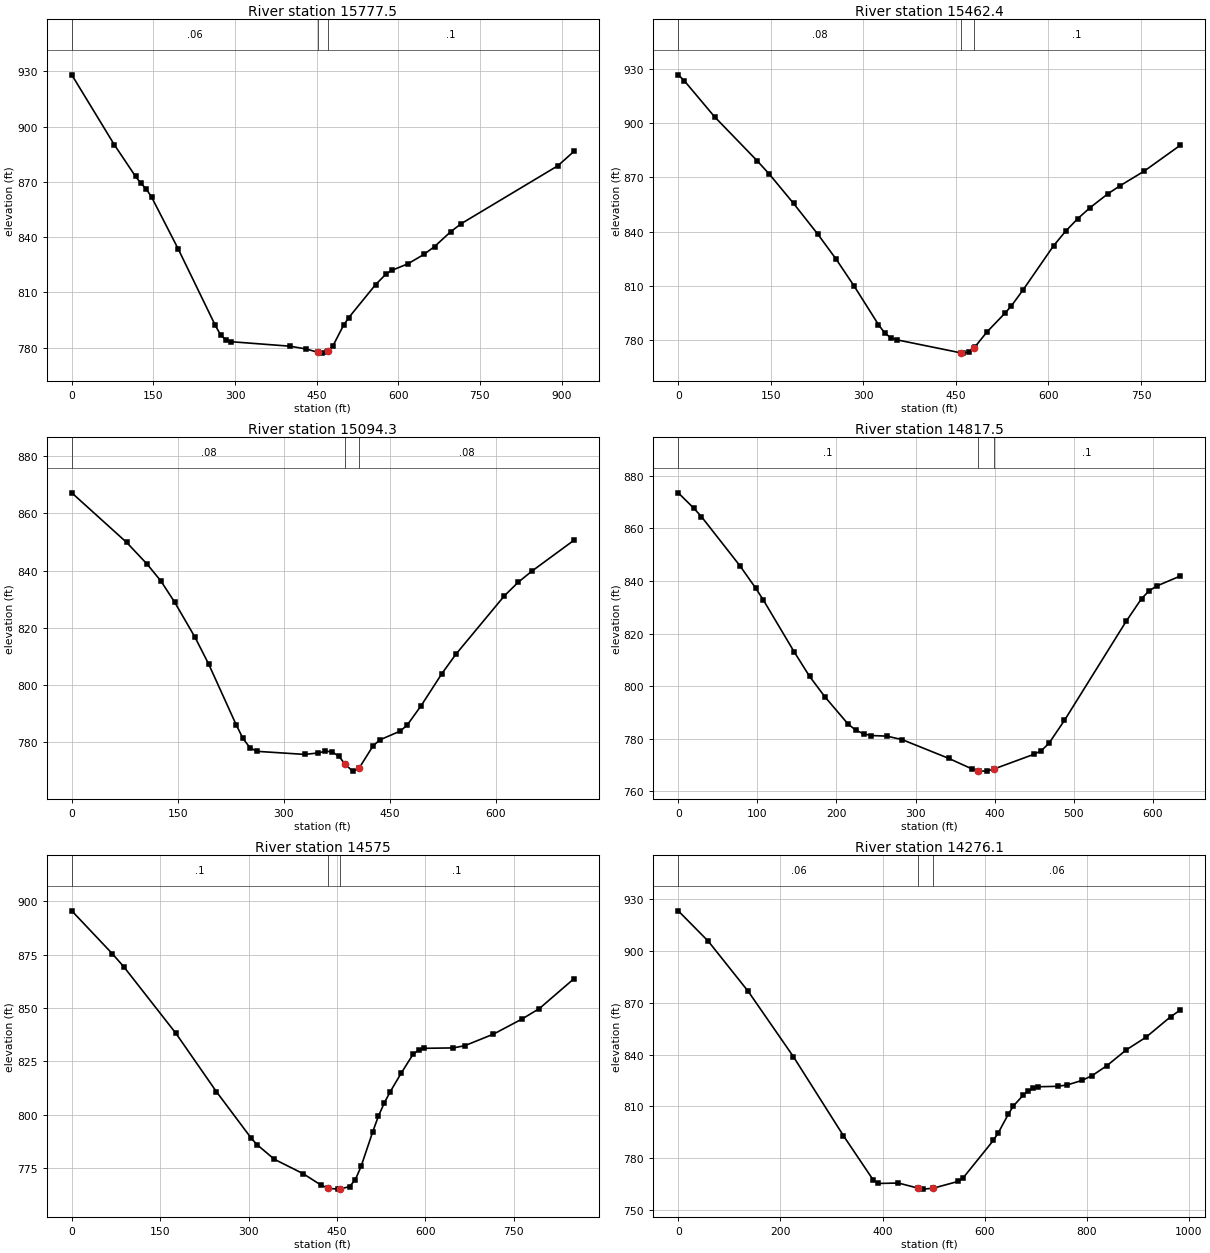
Type RM Length L Ch R = 1 ,15777.5 ,323,315,307.1
XS GIS Cut Line= 3
     1905142.452      562838.658     1905365.502      563135.501
     1905672.016      563593.595
#Sta/Elev= 30
       0  928.09    78.2  890.15   117.2  872.96     127  869.21   136.8  866.13
   146.6  861.79   195.4  833.71   263.8  792.09   273.6   786.9   283.4  784.19
   293.1  783.28   400.8  780.85   430.4  779.36   451.6   777.6   459.9  777.09
   469.7  777.69   471.6  778.31   479.6   780.9   499.3  792.18   509.1  796.42
   558.3  814.28     578  820.18   587.8  821.98   617.4  825.52   646.9  830.63
   666.6  834.92   696.1  842.93   715.8  847.37     893  878.73   922.5  886.49
#Mann= 3 , 0 , 0
       0     .06       0   451.6    .045       0   471.6      .1       0
Bank Sta=451.6,471.6
XS Rating Curve= 0 ,0
Exp/Cntr=0.3,0.1

Type RM Length L Ch R = 1 ,15462.4 ,358.3,367.9,377.6
XS GIS Cut Line= 3
     1904852.956      563113.679     1905067.041      563330.866
     1905467.101      563645.111
#Sta/Elev= 30
       0  926.57     9.8   923.3      59  903.37   127.9  879.13   147.6  871.77
   186.9  855.59   226.3  838.56   255.8  824.87   285.3  809.86   324.5   788.7
   334.3  784.21   344.1  781.49   353.9  780.33   458.6  773.07   461.5  772.96
   471.3  773.62   478.6  775.78   481.1  776.52   500.6  784.74     530  795.17
   539.8  798.99   559.3  808.07   608.2  832.18   627.8  840.26   647.4  847.16
   666.9   853.1   696.3  860.91   715.8  865.29     755  873.38   813.7   887.7
#Mann= 3 , 0 , 0
       0     .08       0   458.6    .045       0   478.6      .1       0
Bank Sta=458.6,478.6
XS Rating Curve= 0 ,0
Exp/Cntr=0.3,0.1

Type RM Length L Ch R = 1 ,15094.3 ,271.3,276.8,282.3
XS GIS Cut Line= 3
     1904726.819      563328.733     1904968.754      563748.502
     1905090.756      563938.742
#Sta/Elev= 30
       0  867.18    77.5  849.89   106.6  842.28     126  836.42   145.4  829.06
   174.4  816.74   193.8  807.33   232.6  786.21   242.2  781.42   251.9  778.22
   261.6   776.9   329.5  775.82   348.8  776.32   358.5  776.94   368.2  776.73
   377.9   775.2   386.5  772.49   397.3  769.98   406.5  770.98   426.4  778.81
     436  780.89   465.1     784   474.8  786.11   494.3   792.8   523.8  804.05
   543.4  810.75   612.2  831.21   631.9  835.98   651.5   839.9   710.5  850.58
#Mann= 3 , 0 , 0
       0     .08       0   386.5    .045       0   406.5     .08       0
Bank Sta=386.5,406.5
XS Rating Curve= 0 ,0
Exp/Cntr=0.3,0.1

Type RM Length L Ch R = 1 ,14817.5 ,243.4,242.4,241.4
XS GIS Cut Line= 2
     1904547.499      563375.841     1904735.155      563982.231
#Sta/Elev= 30
       0  873.48    19.5   867.7    29.3  864.44    78.1  845.73    97.7  837.36
   107.4  832.86   146.5   813.1     166  803.77   185.6  795.91   214.8  785.61
   224.6  783.29   234.4   781.9   244.1  781.27   263.7  781.04   283.2   779.7
   341.8  772.61   371.1  768.62   379.1   767.9   380.9  767.74   390.6  767.78
   399.1  768.54   449.2  774.08     459  775.48   468.8  778.36   488.3  787.01
   566.4   824.7   585.9  833.32   595.7  836.34   605.5  838.14   634.8  841.87
#Mann= 3 , 0 , 0
       0      .1       0   379.1    .045       0   399.1      .1       0
Bank Sta=379.1,399.1
XS Rating Curve= 0 ,0
Exp/Cntr=0.3,0.1

Type RM Length L Ch R = 1 ,14575   ,338.4,298.9,259.8
XS GIS Cut Line= 3
     1904304.982      563409.378     1904480.747      563920.132
     1904724.751      564114.508
#Sta/Elev= 30
       0   895.6    68.8  875.49    88.4  869.34   176.8  838.13   245.5  810.79
   304.4  789.05   314.3  785.97   343.7  779.12   392.8  772.33   422.3  767.12
   435.1  765.47   451.8   765.1   455.1  765.17   471.4  766.28   481.2  769.52
     491  775.73   510.7  791.94   520.5  799.37   530.3  805.46   540.2  810.65
   559.6  819.72   579.2  828.31   588.9  830.36   598.6  831.13   647.4  831.32
   666.9  832.35   715.6  837.77   764.4  844.91   793.6  849.78   852.1  863.71
#Mann= 3 , 0 , 0
       0      .1       0   435.1    .045       0   455.1      .1       0
Bank Sta=435.1,455.1
XS Rating Curve= 0 ,0
Exp/Cntr=0.3,0.1

Type RM Length L Ch R = 1 ,14276.1 ,363.5,383.2,402.6
XS GIS Cut Line= 3
     1903810.836      564177.641     1904446.693      563979.129
     1904724.751       564131.05
#Sta/Elev= 30
       0   923.3    58.8   905.7   137.1  876.61   225.3  838.91   323.3  793.11
     382  767.29   391.8  765.39     431  765.64   470.2  762.63     480  762.11
   499.6  762.67   548.6  766.63   558.4  768.84   617.1  790.38   626.9  794.88
   646.5  805.64   656.3   810.3   675.7  816.61   685.3  818.75   694.9  820.56
   704.5   821.4   742.9  821.66   762.1  822.48   790.9  825.13   810.2  827.83
     839  833.55   877.4   842.8   915.8  850.09   963.8   861.9     983  865.84
#Mann= 3 , 0 , 0
       0     .06       0   470.2    .045       0   499.6     .06       0
Bank Sta=470.2,499.6
XS Rating Curve= 0 ,0
Exp/Cntr=0.3,0.1

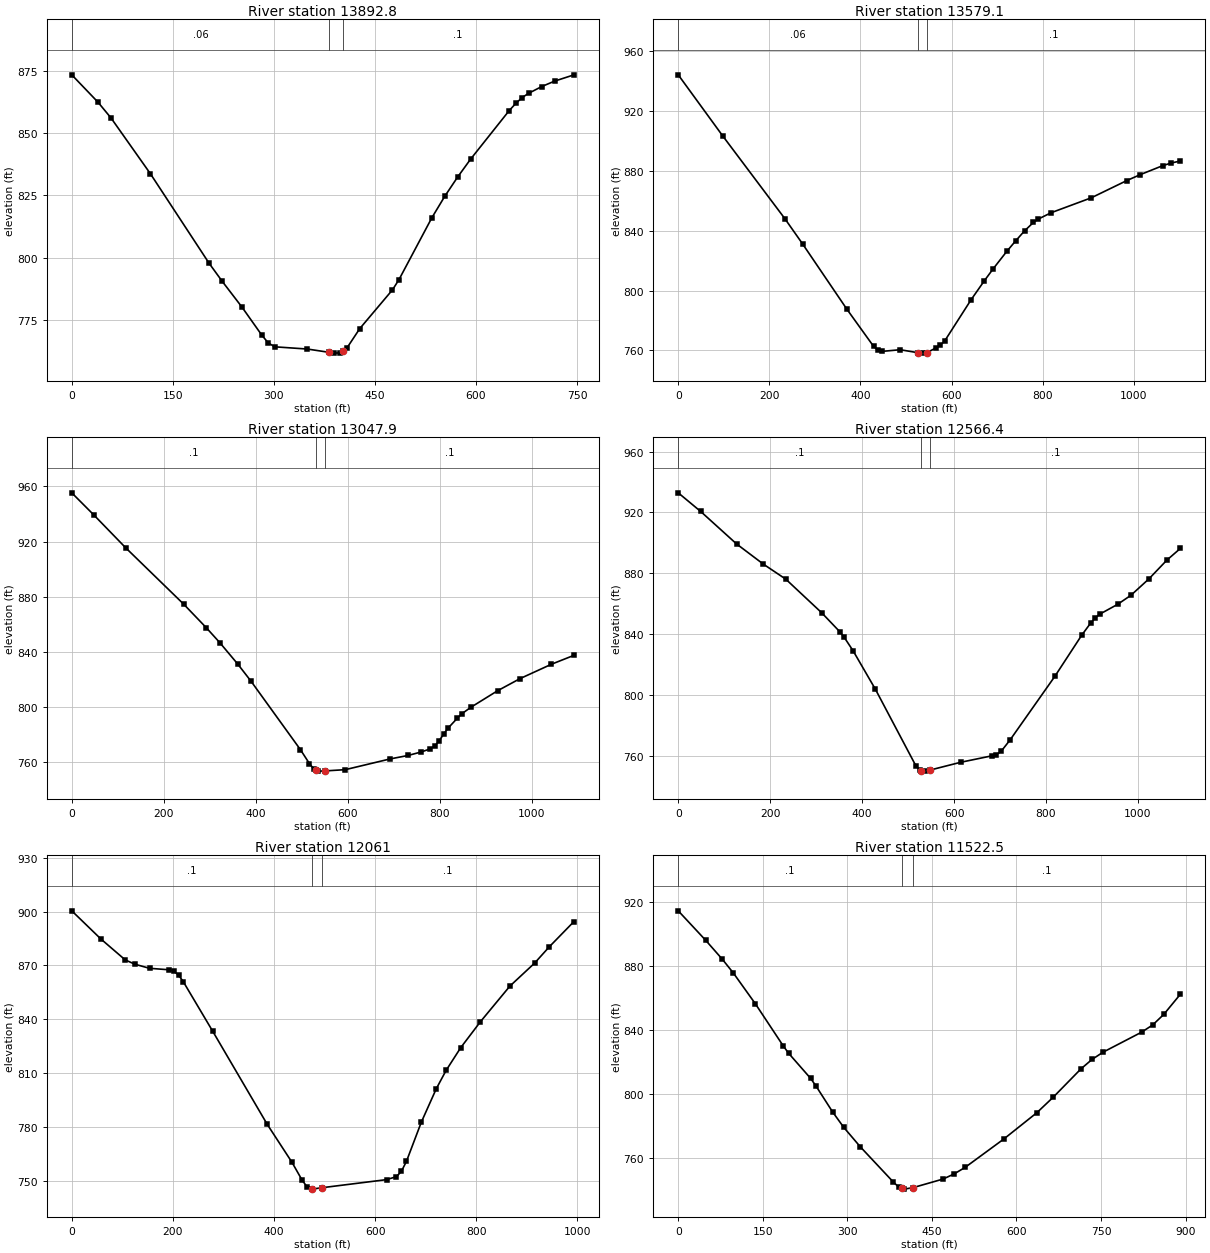
Type RM Length L Ch R = 1 ,13892.8 ,307.4,313.7,320.1
XS GIS Cut Line= 3
      1903945.18      564219.967     1904420.328      564464.552
     1904611.085      564554.502
#Sta/Elev= 30
       0  873.41    38.9  862.42    58.3  856.06   116.6  833.71     204  797.63
   223.5  790.37   252.6  780.09   281.8  768.92   291.5  765.72   301.2  764.12
   349.8  763.22     382   761.9   388.7  761.58   398.4  761.67     402  762.35
   408.1   763.5   427.5  771.43   476.1  787.02   485.8  791.16   534.4  815.92
   553.6  824.56   572.8  832.34   591.9  839.48   649.4  859.06     659  861.89
   668.6  864.28   678.2  865.99   697.4  868.67   716.6  870.87   745.3  873.39
#Mann= 3 , 0 , 0
       0     .06       0     382    .045       0     402      .1       0
Bank Sta=382,402
XS Rating Curve= 0 ,0
Exp/Cntr=0.3,0.1

Type RM Length L Ch R = 1 ,13579.1 ,518.7,531,543.3
XS GIS Cut Line= 3
     1903698.829       564285.26     1904211.413      564735.373
      1904537.61      565000.294
#Sta/Elev= 30
       0  944.08    97.4  903.39   233.9   848.1   272.9  831.21   370.3  787.53
   428.8  762.78   438.5     760   448.3  759.38   487.3  760.47   525.8  758.51
     536   758.2   545.8  758.53   565.2  761.56     575  763.49   584.7  766.16
   643.2  793.95   672.4  806.66   691.9  814.68   721.2  826.09   740.8  833.16
   760.3  839.83   779.9   845.5   789.7  847.61     819  852.01   906.9  861.94
   985.1  873.48  1014.4  877.41  1063.3  883.36  1082.8  885.22  1102.4   886.5
#Mann= 3 , 0 , 0
       0     .06       0   525.8    .045       0   545.8      .1       0
Bank Sta=525.8,545.8
XS Rating Curve= 0 ,0
Exp/Cntr=0.3,0.1

Type RM Length L Ch R = 1 ,13047.9 ,480.3,481.5,482.8
XS GIS Cut Line= 3
     1903511.714      564373.808     1903710.197      564882.454
     1903908.681      565391.099
#Sta/Elev= 30
       0  955.39    48.8  939.03     117  915.53   243.8  874.34   292.5  857.38
   321.8  846.56   360.8  831.03     390  818.42   497.2  768.79   516.8  758.67
   526.5  754.62   531.1  753.91   536.2  753.13   551.1  753.29   594.8  754.19
   692.2  761.98   731.2   764.5   760.5  767.09     780  769.36   789.8  771.46
   799.5   775.3   809.2  780.27     819  784.58   838.5  791.56   848.2  794.78
   867.8  799.48   926.2  811.56     975  820.37  1043.2   830.8    1092  837.26
#Mann= 3 , 0 , 0
       0      .1       0   531.1    .045       0   551.1      .1       0
Bank Sta=531.1,551.1
XS Rating Curve= 0 ,0
Exp/Cntr=0.3,0.1

Type RM Length L Ch R = 1 ,12566.4 ,500.9,505.4,509.8
XS GIS Cut Line= 3
      1903091.65      564545.218     1903264.299      565063.203
     1903436.948      565581.188
#Sta/Elev= 30
       0  932.85    48.8  920.61   126.8  899.28   185.2  885.98     234   876.1
     312  854.04     351   841.7   360.8  837.99   380.2  829.11     429  803.68
   516.8   753.5   526.5  750.47   528.5  750.37   536.2  749.98   548.5  750.74
   614.2  755.79   682.5  760.05   692.2  760.88     702  762.89   721.5  770.37
     819   812.2   877.5  839.27     897  847.27   906.8  850.59   916.5  853.08
   955.5  859.54   984.8  865.58  1023.8  876.33  1062.8  888.64    1092  896.28
#Mann= 3 , 0 , 0
       0      .1       0   528.5    .045       0   548.5      .1       0
Bank Sta=528.5,548.5
XS Rating Curve= 0 ,0
Exp/Cntr=0.3,0.1

Type RM Length L Ch R = 1 ,12061   ,551.4,538.5,525.7
XS GIS Cut Line= 4
     1902733.433      564736.923     1902759.346      565033.721
      1902819.83      565452.456     1902931.945      565700.531
#Sta/Elev= 30
       0  900.43    57.7  884.71   105.7  873.09   124.9  870.67   153.8   868.4
   192.2  867.58   201.8  866.86   211.4   864.6     221  860.75   278.7  833.37
   386.5  781.51   435.7  760.25   455.4  750.46   465.2  746.67   474.6  745.39
     475  745.34   494.6  746.11   622.6  750.63   642.3  752.29   652.1  755.29
     662  760.78   691.5  782.67     721  801.24   740.4  811.46   769.6  824.25
   808.5  838.67   866.8  858.51   915.5  871.27   944.6  880.37   993.2   894.4
#Mann= 3 , 0 , 0
       0      .1       0   474.6    .045       0   494.6      .1       0
Bank Sta=474.6,494.6
XS Rating Curve= 0 ,0
Exp/Cntr=0.3,0.1

Type RM Length L Ch R = 1 ,11522.5 ,332.9,348.5,364
XS GIS Cut Line= 3
     1902107.916      565139.116     1902219.578      565323.152
     1902631.076       565858.72
#Sta/Elev= 30
       0  914.65    48.9  896.15    78.3  884.34    97.8  875.76     137  856.44
   185.9   830.4   195.7  825.64   234.8  809.91   244.6  804.99     274  788.83
   293.6  779.27   322.9  767.14   381.7  745.03   391.4  741.83   396.8  741.17
   401.2  740.64   416.8   741.6   469.8  746.94   489.3  750.11   508.9  754.22
   577.4  771.92   636.2  788.42   665.5  798.21   714.5  815.85     734  821.71
   753.6  826.26   822.1  838.79   841.7  843.29   861.3  849.86   890.7  862.45
#Mann= 3 , 0 , 0
       0      .1       0   396.8    .045       0   416.8      .1       0
Bank Sta=396.8,416.8
XS Rating Curve= 0 ,0
Exp/Cntr=0.3,0.1

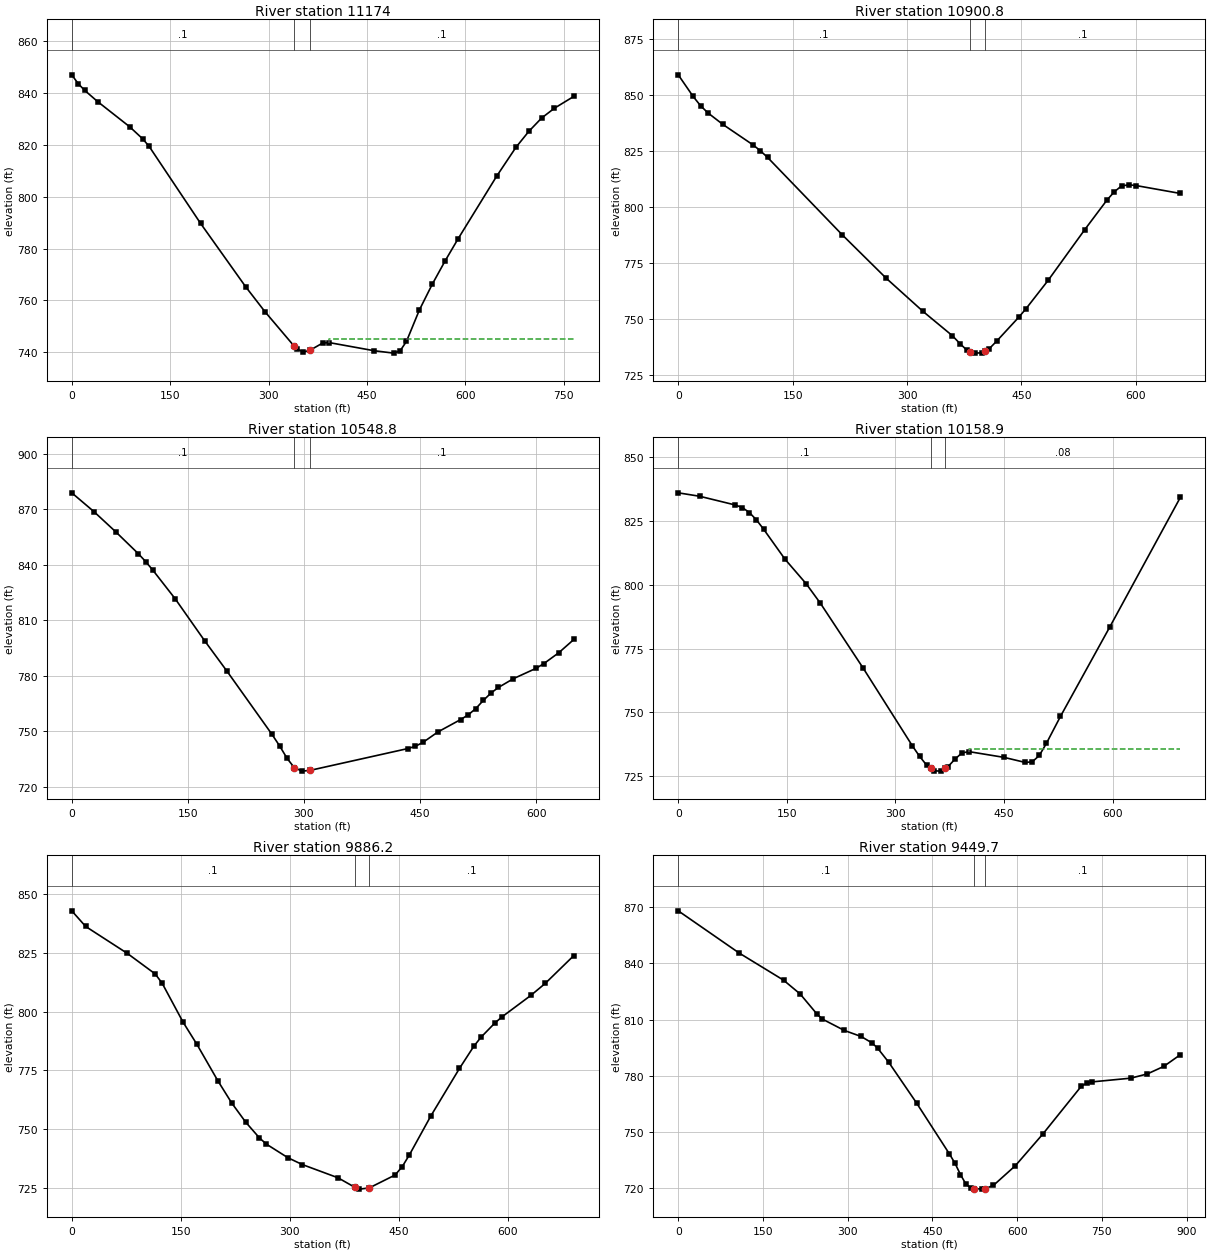
Type RM Length L Ch R = 1 ,11174   ,256.3,273.2,290.1
XS GIS Cut Line= 2
       1902053.7      565320.632     1902090.921      566085.211
#Sta/Elev= 30
       0  847.02     9.8  843.61    19.6  841.05    39.3  836.72    88.3  826.98
     108  822.35   117.8  819.47   196.3  789.74     265  765.31   294.4  755.69
   339.5  742.22   343.5  741.15   353.3  740.11   363.1  740.75   382.7  743.58
   392.6  743.72   461.2  740.58   490.7  739.66   500.5   740.5   510.3  744.18
     530  756.31   549.6  766.22   569.2  775.23   588.8  783.68   647.7  807.87
   677.2  819.05   696.8  825.19   716.4  830.36     736  834.16   765.5   838.7
#Mann= 3 , 0 , 0
       0      .1       0   339.5    .045       0   363.1      .1       0
#XS Ineff= 2 , 0
                          392.51          744.99
Permanent Ineff=
       F       F
Bank Sta=339.5,363.1
XS Rating Curve= 0 ,0
Exp/Cntr=0.3,0.1

Type RM Length L Ch R = 1 ,10900.8 ,375.3,351.9,328.5
XS GIS Cut Line= 3
     1902026.236      565286.965     1901898.613      565483.474
     1901653.575      565829.318
#Sta/Elev= 30
       0     859    19.5  849.37    29.3   845.2      39     842    58.6  836.85
    97.6  827.84   107.4  825.21   117.2  822.12   214.8  787.69   272.8   768.2
     321  753.42   359.5  742.58   369.2  739.12   378.8  736.05   382.8  735.55
   388.4  734.84   398.1  734.97   402.8  735.87   407.7   736.8   417.3  740.14
   446.2  750.78   455.9  754.65   484.8  767.25   532.9  789.92   561.8  803.02
   571.5  806.77   581.1  809.42   590.7  809.94   600.4  809.59   658.2  806.08
#Mann= 3 , 0 , 0
       0      .1       0   382.8    .045       0   402.8      .1       0
Bank Sta=382.8,402.8
XS Rating Curve= 0 ,0
Exp/Cntr=0.3,0.1

Type RM Length L Ch R = 1 ,10548.8 ,369.3,390,410.6
XS GIS Cut Line= 3
     1901521.687      565185.642     1901512.446      565385.769
     1901645.821      565813.809
#Sta/Elev= 30
       0  878.81    28.6  868.67    57.2  857.59    85.9  845.96    95.4  841.71
   104.9  836.96   133.6  821.58   171.7  798.88   200.3   782.6   258.8  748.26
   268.6  742.05   278.3   735.3   287.7  730.25   297.8  728.47   307.7  728.86
   434.3  740.67     444   741.9   453.8  744.01   473.2  749.67   502.5  756.35
   512.2  758.86     522  762.26   531.7  766.63   541.5  770.61   551.2  773.67
   570.7  778.43     600  784.03   609.7  786.48   629.2  792.41   648.7  799.59
#Mann= 3 , 0 , 0
       0      .1       0   287.7    .045       0   307.7      .1       0
Bank Sta=287.7,307.7
XS Rating Curve= 0 ,0
Exp/Cntr=0.3,0.1

Type RM Length L Ch R = 1 ,10158.9 ,264.5,272.7,281
XS GIS Cut Line= 3
     1901357.811      565157.209     1901233.742      565380.535
      1901016.62      565761.015
#Sta/Elev= 30
       0  835.99    29.5  834.65    78.6  831.24    88.4  830.24    98.3  828.28
   108.1  825.37   117.9  821.77   147.4  810.03   176.9  800.33   196.5   792.7
   255.5  767.34   323.6  736.84   333.4   732.8   343.1  729.37   348.9  728.04
   352.8  727.15   362.6  727.01   368.9  728.07   372.3  728.64     382  731.61
   391.8  734.12   401.5  734.65   450.2  732.39   479.4  730.41   489.1  730.66
   498.8  733.13   508.6  737.88     528  748.42   596.2  783.47   693.6  834.18
#Mann= 3 , 0 , 0
       0      .1       0   348.9    .045       0   368.9     .08       0
#XS Ineff= 2 , 0
                          401.61          735.77
Permanent Ineff=
       F       F
Bank Sta=348.9,368.9
XS Rating Curve= 0 ,0
Exp/Cntr=0.3,0.1

Type RM Length L Ch R = 1 ,9886.2  ,446.3,436.5,426.7
XS GIS Cut Line= 3
     1901223.919      564991.266     1901071.999      565212.071
     1900754.523       565491.68
#Sta/Elev= 30
       0  842.82    19.1  836.18    76.6   824.7   114.9  815.98   124.4  812.05
   153.2   795.5   172.3  786.05     201  770.62   220.2  761.12   239.3  753.04
   258.4  746.27     268  743.64   297.5  737.88   317.2  734.99   366.4  729.36
   389.4  725.35   395.9  724.53   409.4  725.03   445.1  730.54     455  734.14
   464.8  739.13   494.3  755.66   533.7  775.85   553.3   785.2   563.2  789.06
   582.8  795.27   592.7  797.86     632  806.89   651.7  811.96   691.1  823.81
#Mann= 3 , 0 , 0
       0      .1       0   389.4    .045       0   409.4      .1       0
Bank Sta=389.4,409.4
XS Rating Curve= 0 ,0
Exp/Cntr=0.3,0.1

Type RM Length L Ch R = 1 ,9449.7  ,331.6,321.2,310.8
XS GIS Cut Line= 3
     1900996.459      564610.786     1900715.234      564925.096
     1900506.384      565342.797
#Sta/Elev= 30
       0  868.14   107.9  845.56   186.4  831.07   215.8  823.68   245.2  813.08
     255  810.27   294.2  804.15   323.7  800.95   343.3  797.46   353.1  794.64
   372.7  787.12   421.8  765.42   480.1  738.12   489.9  733.17   499.6  727.11
   509.3     722     519  719.77   522.7  719.64   538.5  719.32   542.7   719.5
     558  721.33   596.9  731.88   645.5   748.8   713.6  774.37   723.4  776.02
   733.1  776.68   801.2  778.66   830.4  780.92   859.6  784.96   888.8  791.19
#Mann= 3 , 0 , 0
       0      .1       0   522.7    .045       0   542.7      .1       0
Bank Sta=522.7,542.7
XS Rating Curve= 0 ,0
Exp/Cntr=0.3,0.1

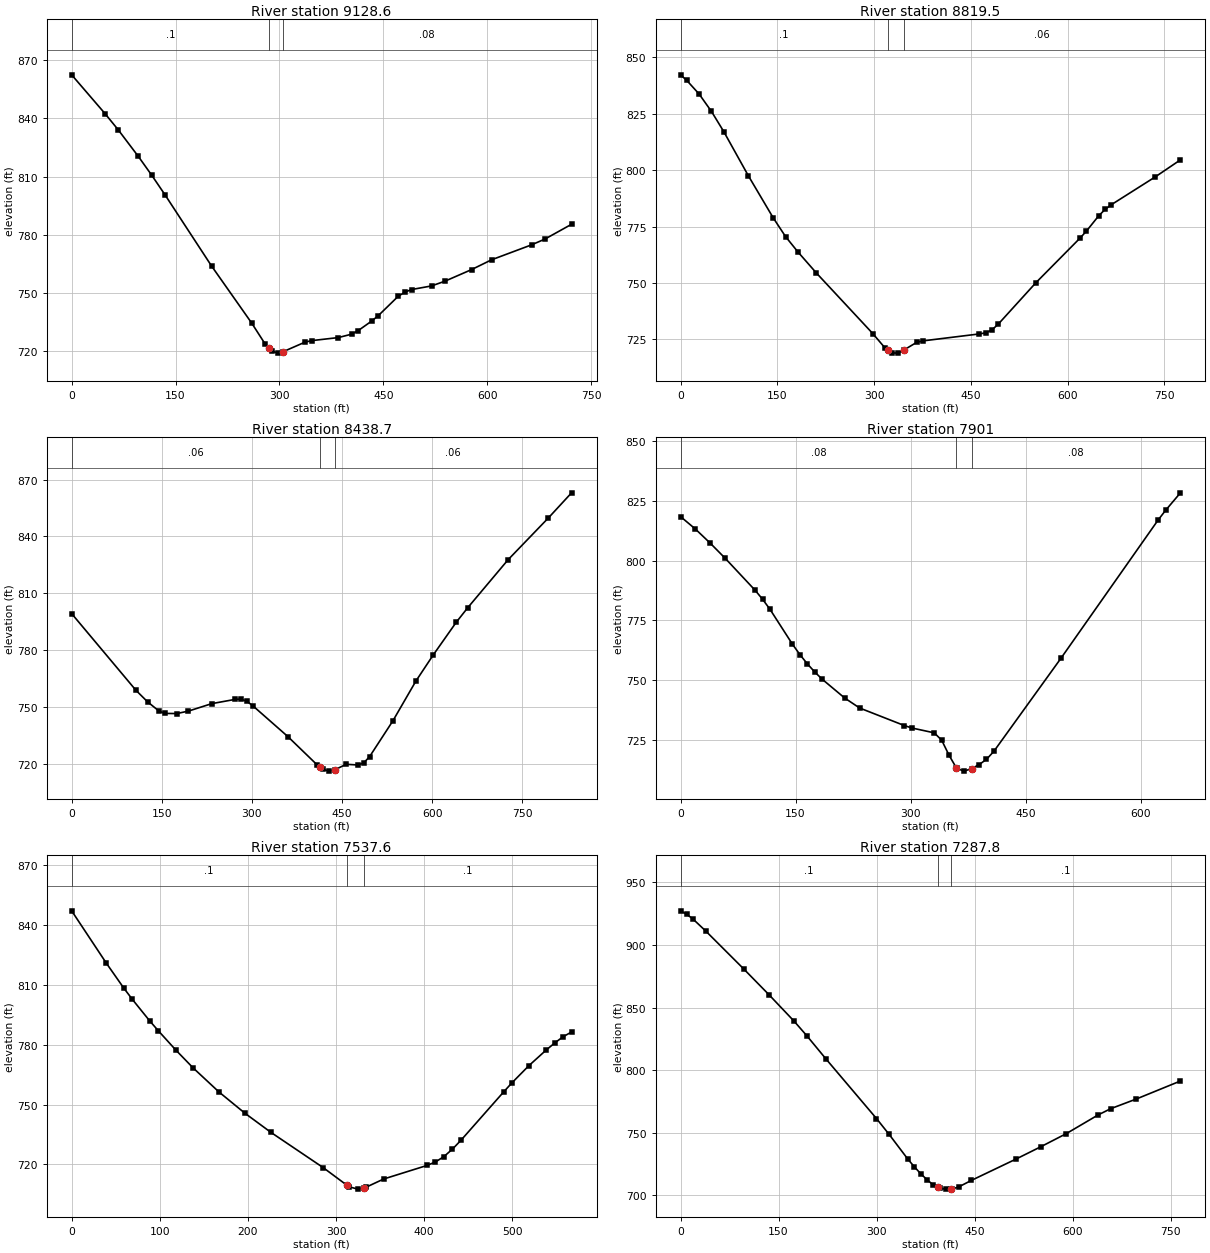
Type RM Length L Ch R = 1 ,9128.6  ,333.4,309,284.7
XS GIS Cut Line= 4
     1900288.809      564647.555     1900366.353      564844.515
     1900357.048      565036.823     1900499.728      565320.632
#Sta/Elev= 30
       0  862.48    48.1   842.5    67.4  834.03    96.2  820.42   115.5  810.75
   134.7  800.63     202  763.86   259.8   734.5   279.1  723.77   285.1  721.37
   288.7  719.93   298.3   718.9   305.1  719.59   336.8  724.54   346.4  725.34
     385  726.92   404.2  728.67   413.8  730.52   433.1  735.41   442.7   738.2
   471.6  748.24   481.2  750.36   490.8   751.7   519.7  753.57     539  756.01
   577.5     762   606.4  767.05   664.1  774.76   683.4  777.74   721.9  785.38
#Mann= 3 , 0 , 0
       0      .1       0   285.1    .045       0   305.1     .08       0
Bank Sta=285.1,305.1
XS Rating Curve= 0 ,0
Exp/Cntr=0.3,0.1

Type RM Length L Ch R = 1 ,8819.5  ,360.1,380.8,401.5
XS GIS Cut Line= 3
     1899950.138      564850.654     1900065.936      565049.165
     1900496.044      565384.153
#Sta/Elev= 30
       0  842.27     9.6  839.82    28.7   833.8    47.9  826.07      67  817.12
   105.3  797.44   143.6   778.9   162.8  770.56   181.9  763.77   210.7  754.37
     298  727.55   317.4  721.04   320.9   720.3   327.2  718.96   336.9  718.86
   346.6   720.3   366.1  723.63   375.8  724.29   463.5  727.38   473.2  727.87
   482.9  729.17   492.7  731.75   551.1  750.13   619.2  769.82     629  772.88
   648.4  779.78   658.2  782.58   667.9  784.68     736  797.01     775  804.56
#Mann= 3 , 0 , 0
       0      .1       0   320.9    .045       0   346.6     .06       0
Bank Sta=320.9,346.6
XS Rating Curve= 0 ,0
Exp/Cntr=0.3,0.1

Type RM Length L Ch R = 1 ,8438.7  ,534.7,537.6,540.6
XS GIS Cut Line= 3
     1899784.712      564850.654     1899830.204      565373.814
     1899886.035      565675.717
#Sta/Elev= 30
       0  799.24     107  758.74   126.4  752.63   145.9  747.64   155.6  746.52
     175  746.44   194.5  747.76   233.4   751.7   272.3  753.94     282  754.08
   291.7   752.9   301.5  750.58   359.8  734.32   408.4  719.41   413.8   718.1
   418.2  717.03   427.9  716.03   437.6  716.69   457.1  719.64   476.5  719.28
   486.2  720.37     496   723.7   534.7  742.57   573.1  763.63   601.9   777.4
   640.3  794.71   659.5  802.42   726.6  827.74   793.8  849.86   832.2  863.06
#Mann= 3 , 0 , 0
       0     .06       0   413.8    .045       0   437.6     .06       0
Bank Sta=413.8,437.6
XS Rating Curve= 0 ,0
Exp/Cntr=0.3,0.1

Type RM Length L Ch R = 1 ,7901    ,361.4,363.4,365.5
XS GIS Cut Line= 3
     1899323.069      565022.284     1899306.527      565479.273
     1899298.256      565673.649
#Sta/Elev= 30
       0  818.48    19.5  813.23    38.9   807.3    58.4  800.97    97.3  787.63
     107  783.88   116.8  779.61   145.9  765.09   155.7  760.72   165.4  756.84
   175.1  753.43   184.9  750.38     214  742.58   233.5  738.39   291.9  731.04
   301.6  730.03   330.8     728   340.5  724.94   350.3  718.52   359.4  713.47
     360  713.14   369.7  711.98   379.4  713.01   389.2  714.68   398.9   716.9
   408.6  720.28   496.2  759.27   622.7  817.03   632.4  821.06   651.8  828.41
#Mann= 3 , 0 , 0
       0     .08       0   359.4    .045       0   379.4     .08       0
Bank Sta=359.4,379.4
XS Rating Curve= 0 ,0
Exp/Cntr=0.3,0.1

Type RM Length L Ch R = 1 ,7537.6  ,268.7,249.7,230.8
XS GIS Cut Line= 3
     1898992.734      564995.402     1898947.242      565386.221
     1898947.242      565559.919
#Sta/Elev= 30
       0  847.18    39.4  820.89      59  808.51    68.9  802.73    88.5  791.99
    98.4  786.97     118  777.42   137.7  768.42   167.2  756.28   196.7   745.6
   226.2     736   285.3  718.38   312.1  709.58   314.8  708.75   324.6  707.56
   332.1  708.36   334.4   708.6   354.1  712.65   403.1  719.43   412.8   721.2
   422.4  723.89   432.1  727.66   441.7  732.07     490  756.26   499.6  760.91
   518.9  769.55   538.2  777.26   547.9  780.82   557.5  783.99   567.2  786.39
#Mann= 3 , 0 , 0
       0      .1       0   312.1    .045       0   332.1      .1       0
Bank Sta=312.1,332.1
XS Rating Curve= 0 ,0
Exp/Cntr=0.3,0.1

Type RM Length L Ch R = 1 ,7287.8  ,316.7,291.7,266.7
XS GIS Cut Line= 3
     1898417.878      565084.318     1898610.186      565195.981
     1898932.767      565632.293
#Sta/Elev= 30
       0  927.28     9.7  924.46    19.3  920.61    38.7   911.1    96.7  880.86
   135.4  860.23     174     839   193.4   827.4   222.4  809.05   299.9  761.32
   319.3  748.61   348.3  728.61     358  722.66   367.7  717.17   377.4  712.39
   387.1  708.11   393.4  706.41   396.8  705.49   406.5  704.93   413.4  705.06
   416.2  705.11   425.8  706.73   445.2  711.93   513.1  728.87   551.8  738.91
   590.6  749.34     639   764.2   658.4  769.22   697.2  776.87     765  791.31
#Mann= 3 , 0 , 0
       0      .1       0   393.4    .045       0   413.4      .1       0
Bank Sta=393.4,413.4
XS Rating Curve= 0 ,0
Exp/Cntr=0.3,0.1

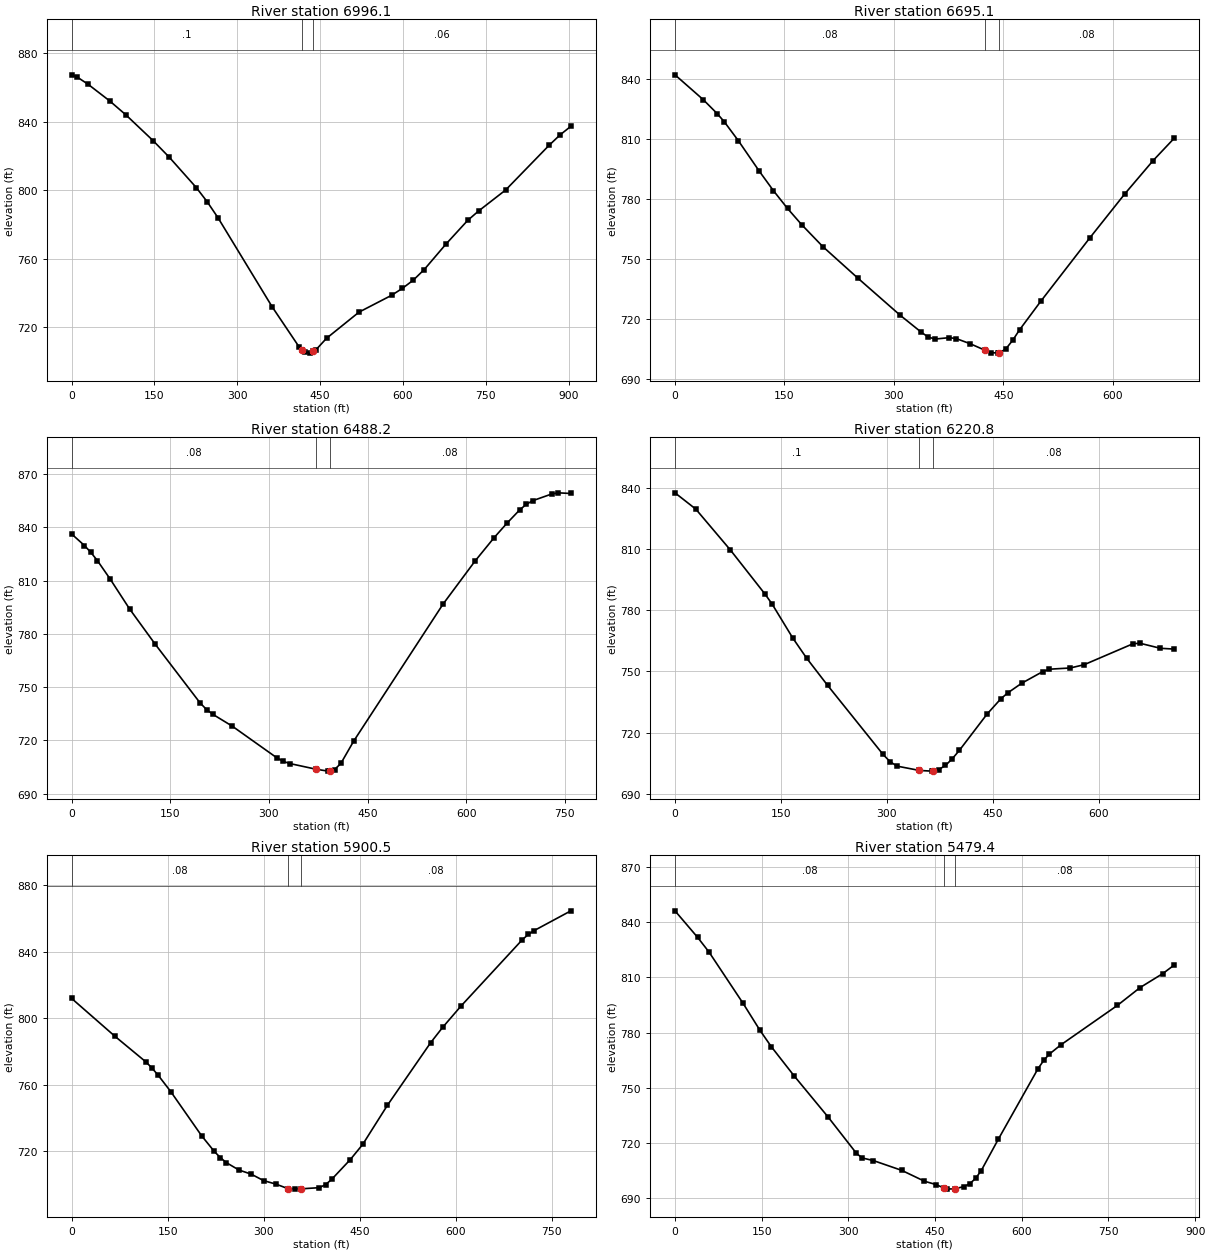
Type RM Length L Ch R = 1 ,6996.1  ,288.4,300.8,313
XS GIS Cut Line= 3
     1898190.417       565615.75     1898710.023      565585.831
     1899025.819      565803.922
#Sta/Elev= 30
       0  867.29     9.8  866.04    29.5  861.84    68.7  852.11    98.2  843.92
   147.3  828.92   176.8  819.18   225.9  801.39   245.5  793.16   265.1  783.81
   363.3  731.73   412.4  708.18   417.4  706.81   422.3  705.47  432.16  704.75
   437.4  705.78   441.9  706.49   461.6   713.4   520.5   728.7   579.5  738.53
   599.2  742.61   618.9  747.41   638.6  753.56   677.9  768.41   717.3  782.27
     737  787.75   786.2  800.07   864.9  826.18   884.6   832.2   904.2  837.24
#Mann= 3 , 0 , 0
       0      .1       0   417.4    .045       0   437.4     .06       0
Bank Sta=417.4,437.4
XS Rating Curve= 0 ,0
Exp/Cntr=0.3,0.1

Type RM Length L Ch R = 1 ,6695.1  ,186.9,206.9,226.8
XS GIS Cut Line= 3
     1898252.517      565671.129     1898511.512      565838.623
     1898854.254      565992.159
#Sta/Elev= 30
       0     842    38.6  829.64    57.8  822.64    67.5  818.58    86.8  809.12
   115.7  793.79   134.9  784.15   154.2  775.28   173.5  767.22   202.4  756.29
   250.6  740.48   308.4  722.01   337.3  713.54     347  711.05   356.6  710.09
   375.8  710.79   385.5   710.3   404.7  707.71   424.2  704.59   433.6  703.32
   443.2  703.06   444.2  703.26   452.9     705   462.5  709.38   472.1   714.7
     501  728.88   568.4  760.62   616.6  782.72   655.1  799.21     684  810.36
#Mann= 3 , 0 , 0
       0     .08       0   424.2    .045       0   444.2     .08       0
Bank Sta=424.2,444.2
XS Rating Curve= 0 ,0
Exp/Cntr=0.3,0.1

Type RM Length L Ch R = 1 ,6488.2  ,265.6,267.5,269.3
XS GIS Cut Line= 3
     1898252.452      565702.599     1898419.946      565880.432
     1898595.711      566364.303
#Sta/Elev= 30
       0  836.32    19.5  829.82    29.3  825.91    39.1  821.36    58.6  810.92
      88  794.14     127  774.23   195.4  741.06   205.2  737.35     215   734.6
   244.3  727.98   312.3  710.08     322  708.12   331.7  706.93   372.2  703.68
     390  702.65   392.2  702.84   399.7   703.5   409.4  707.01   428.8  719.53
   564.8  796.83   613.4  821.07   642.5   834.3     662  842.43   681.4  849.95
   691.1  852.97   700.8  855.05     730  858.87   739.7  859.52   759.1  859.15
#Mann= 3 , 0 , 0
       0     .08       0   372.2    .045       0   392.2     .08       0
Bank Sta=372.2,392.2
XS Rating Curve= 0 ,0
Exp/Cntr=0.3,0.1

Type RM Length L Ch R = 1 ,6220.8  ,316.2,319.9,323.7
XS GIS Cut Line= 2
     1898117.591      565751.774     1898308.348      566432.606
#Sta/Elev= 30
       0   837.4    29.5  829.41    78.6  809.34   127.7  787.71   137.5  782.95
   166.9  766.24   186.6  756.35     216  743.16   294.6  709.29   304.4  705.79
   314.2  703.57     346  701.44   363.4   701.1     366  701.29   373.2  701.81
     383  703.86   392.8  707.22   402.6  711.21   441.9  729.02   461.6  736.58
   471.4  739.45     491  744.15   520.5  749.79   530.3  751.02   559.8  751.62
   579.4  753.22   648.1  763.41     658  763.77   687.4  761.26     707  760.87
#Mann= 3 , 0 , 0
       0      .1       0     346    .045       0     366     .08       0
Bank Sta=346,366
XS Rating Curve= 0 ,0
Exp/Cntr=0.3,0.1

Type RM Length L Ch R = 1 ,5900.5  ,402.4,421,439.4
XS GIS Cut Line= 3
     1897865.768      565849.414     1897936.074       566376.71
     1897979.499      566620.714
#Sta/Elev= 30
       0  811.79    67.7     789   116.1  773.58   125.7  769.84   135.4  765.47
   154.8  755.77   203.1  729.15   222.5  719.92   232.1  716.11   241.8  712.99
   261.2  708.61   280.5   706.1   299.8  702.22   319.2  700.09   337.8  697.41
   348.2  697.09   357.8  697.25   386.9  697.97   396.6   699.8   406.2  702.97
   435.2  714.83   454.6  723.96   493.3  747.56   560.6  785.09   579.6  794.43
   608.2  807.22   703.5  846.92   713.1  850.25   722.6  852.63   779.8  864.48
#Mann= 3 , 0 , 0
       0     .08       0   337.8    .045       0   357.8     .08       0
Bank Sta=337.8,357.8
XS Rating Curve= 0 ,0
Exp/Cntr=0.3,0.1

Type RM Length L Ch R = 1 ,5479.4  ,191.3,179.4,167.8
XS GIS Cut Line= 3
      1897845.09      565698.463     1897658.986      565913.517
     1897328.133      566389.117
#Sta/Elev= 30
       0  846.13    39.2   831.7    58.8  823.78   117.7  795.94   147.1   781.2
   166.7  772.32   205.9  756.58   264.8  734.18   313.9  714.44   323.7  711.93
   343.3  710.48   392.4  705.16   431.7  699.26   451.3  697.49   465.6  695.56
     471  694.98   484.5  695.22   500.4  696.39   510.2  697.95   520.1  700.82
   529.9  705.06   559.4  722.08   628.1  760.39   637.9  764.87   647.7   768.3
   667.4  773.28   765.6   794.8   804.8  804.47   844.1  812.07   863.8   816.7
#Mann= 3 , 0 , 0
       0     .08       0   465.6    .045       0   484.5     .08       0
Bank Sta=465.6,484.5
XS Rating Curve= 0 ,0
Exp/Cntr=0.3,0.1