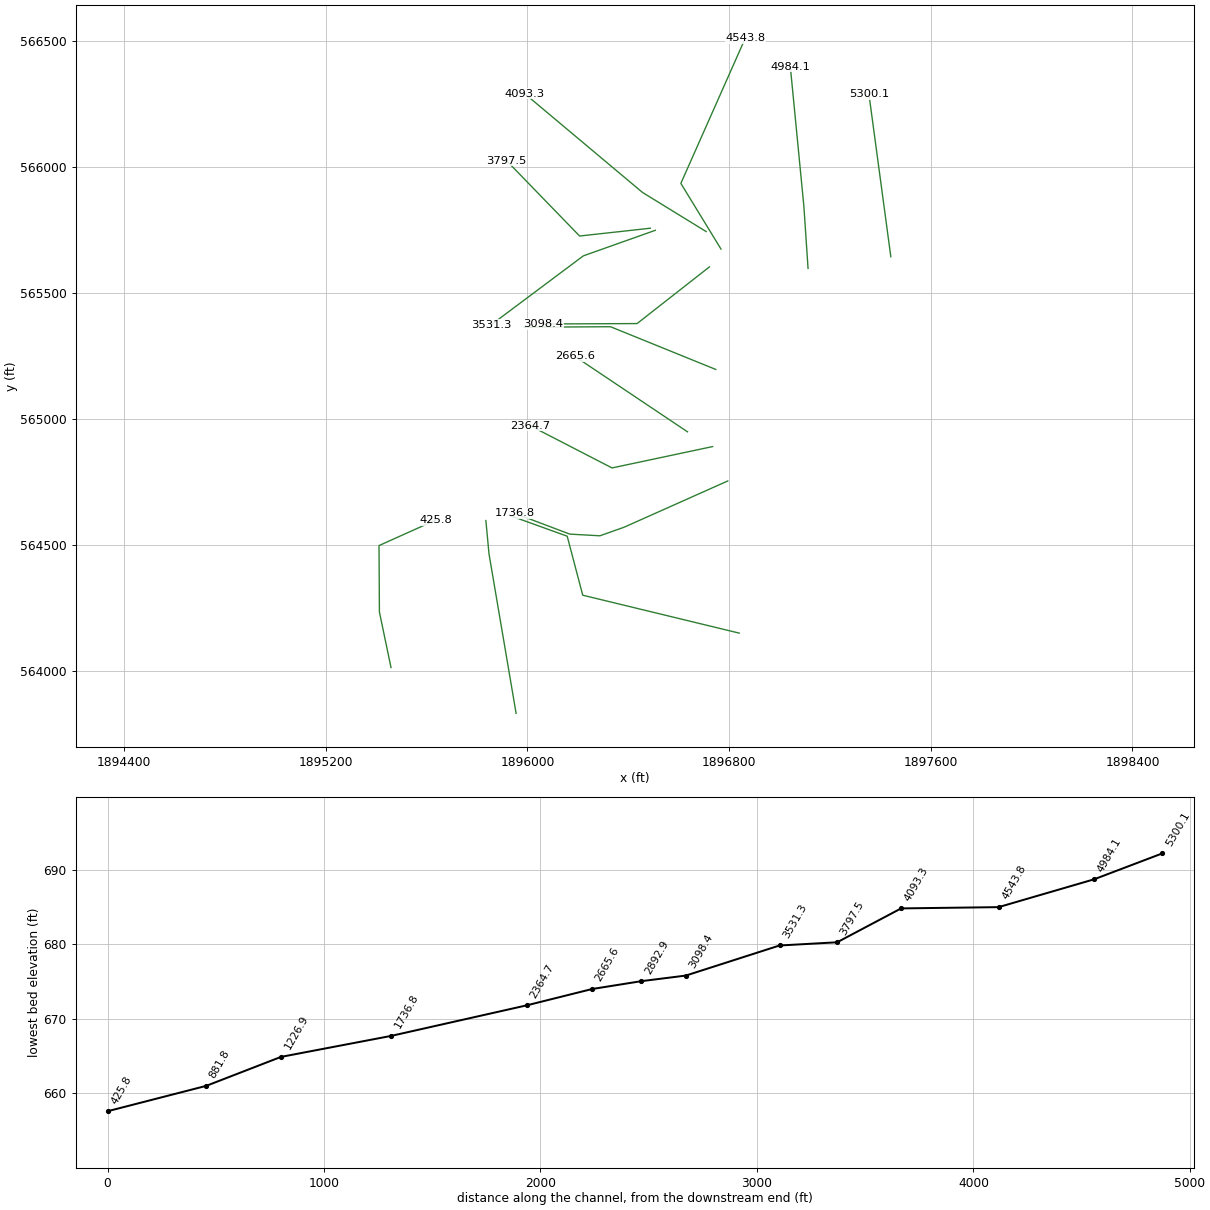
HEC-RAS study PigeonRun.prj: PigeonRun

--- PigeonRun.g01 (geometry) --- (continued)

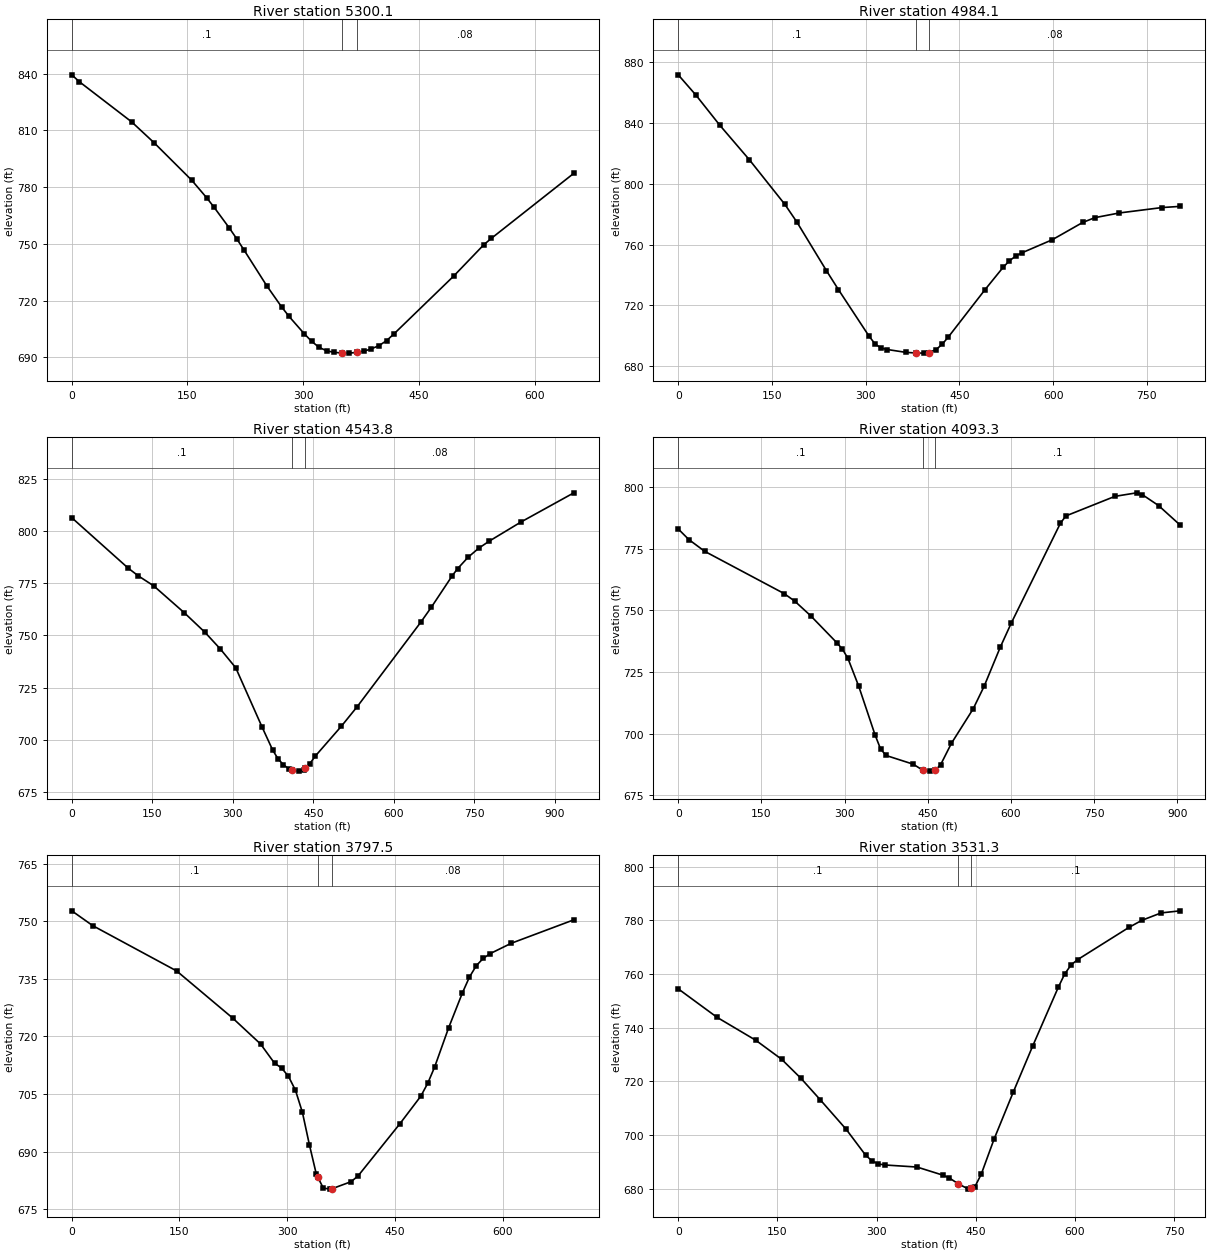
Type RM Length L Ch R = 1 ,5300.1  ,316.9,315.9,314.7
XS GIS Cut Line= 2
     1897441.411      565643.213     1897354.563      566288.375
#Sta/Elev= 30
       0  839.45     9.7  835.84    77.7  814.53   106.9  803.44   155.5  783.69
   174.9  774.39   184.6  769.32     204  758.54   213.8  752.74   223.5  746.64
   252.6  727.95     272  716.67   281.8  711.56   301.2  702.53   310.9  698.46
   320.6  695.24   330.4  693.42   340.1  692.56   349.8  692.29  359.37  692.17
   369.2  692.53   378.9  693.22   388.6  694.46   398.4  696.15   408.1  698.76
   417.8  702.36   495.5  733.07   534.4  749.59   544.1  752.93     651  787.34
#Mann= 3 , 0 , 0
       0      .1       0   349.8    .045       0   369.2     .08       0
Bank Sta=349.8,369.2
XS Rating Curve= 0 ,0
Exp/Cntr=0.3,0.1

Type RM Length L Ch R = 1 ,4984.1  ,453.3,440.4,427.4
XS GIS Cut Line= 3
     1897113.079       565597.14     1897096.537      565843.211
     1897042.773      566397.389
#Sta/Elev= 30
       0  871.47    28.5  858.06    66.4  838.42   113.8   815.7   170.7  786.34
   189.7  774.88   237.1  742.88   256.4  730.36   305.2   699.9     315  694.69
   324.8  691.99   334.5  691.07   363.8  689.22   380.8  688.76   393.2  688.69
   400.8  689.04   412.7  691.04   422.4  694.54   432.2  699.29   490.8  730.32
   520.1  745.16   529.9   749.3   539.7  752.35   549.4  754.47   598.3  763.11
   647.1  774.49   666.6  777.66   705.7  780.74   774.1   784.3   803.4  785.08
#Mann= 3 , 0 , 0
       0      .1       0   380.8    .045       0   400.8     .08       0
Bank Sta=380.8,400.8
XS Rating Curve= 0 ,0
Exp/Cntr=0.3,0.1

Type RM Length L Ch R = 1 ,4543.8  ,417.4,450.2,483.1
XS GIS Cut Line= 3
     1896767.752      565673.649     1896608.529      565934.195
     1896863.832      566509.887
#Sta/Elev= 30
       0  806.29     105  782.16     124  778.43   152.7  773.64   209.9  760.71
   248.1  751.41   276.7  743.44   305.4  734.44   354.6  705.98   374.2  695.04
   384.1  690.89   393.9  688.09   403.8  686.12  409.48  685.49   423.4  684.97
   433.3  685.74  435.07  686.27   443.1  688.42     453     692   502.2  706.49
   531.7  715.86   649.8  756.18   669.4  763.32   708.8  778.57   718.6   781.9
   738.3   787.4     758   791.7   777.7   795.1   836.7  804.24   935.1   818.2
#Mann= 3 , 0 , 0
       0      .1       0  409.48    .045       0  435.07     .08       0
Bank Sta=409.48,435.07
XS Rating Curve= 0 ,0
Exp/Cntr=0.3,0.1

Type RM Length L Ch R = 1 ,4093.3  ,297.7,295.6,293.5
XS GIS Cut Line= 3
     1896708.819       565743.18     1896456.544      565898.267
     1895989.643       566289.97
#Sta/Elev= 30
       0     783    19.1   778.7    47.8  773.92     191   756.8   210.2  753.72
   238.8  747.82   286.6  736.73   296.1  734.27     306  730.56   325.6   719.2
   355.1  699.43   364.9  693.82   374.8  691.15   423.9  687.61  441.35  685.13
   453.4   684.8   463.8  685.26   473.1  687.32   492.7  696.06     532  710.06
   551.7  719.19   581.2  735.23   600.9  744.93   689.3  785.31   699.2  788.28
   787.6  796.22   826.9  797.65   836.8  796.95   866.3   792.5   905.6  784.51
#Mann= 3 , 0 , 0
       0      .1       0  441.35    .045       0   463.8      .1       0
Bank Sta=441.35,463.8
XS Rating Curve= 0 ,0
Exp/Cntr=0.3,0.1

Type RM Length L Ch R = 1 ,3797.5  ,229.6,266.2,302.8
XS GIS Cut Line= 3
     1896487.626      565756.427     1896206.919      565725.409
     1895916.906      566024.727
#Sta/Elev= 30
       0  752.72    29.2  748.86   146.1  737.06     224  724.81   262.9  718.05
   282.4  713.04   292.1  711.82   301.8  709.61   311.5  706.01   321.2  700.24
   330.9  691.83   340.6  684.13   342.8  683.31   350.3  680.52     360  680.26
   362.8  680.39     389   682.2   398.7   683.7   456.9  697.27     486  704.44
   495.6  707.77   505.3  712.03   524.7  722.21   544.1   731.4   553.8  735.47
   563.5  738.48   573.2  740.37   582.9   741.6     612  744.27   699.2  750.38
#Mann= 3 , 0 , 0
       0      .1       0   342.8    .045       0   362.8     .08       0
Bank Sta=342.8,362.8
XS Rating Curve= 0 ,0
Exp/Cntr=0.3,0.1

Type RM Length L Ch R = 1 ,3531.3  ,433.3,432.8,432.2
XS GIS Cut Line= 3
     1896507.206      565748.091     1896221.846      565646.767
     1895856.422      565373.362
#Sta/Elev= 30
       0  754.48    58.6  743.88   117.2  735.32   156.3  728.24   185.6  721.12
   214.9  713.09     254  702.11   283.3  692.49     293  690.35   302.8  689.21
   312.5  688.83   361.1  688.06   399.9  685.06   409.6  684.04   423.3  681.84
   438.8  679.83   443.3  680.22   448.5  680.67   458.2   685.4   477.6  698.48
   506.7  716.05   535.9  733.12   574.7  755.07   584.4  760.04   594.1  763.41
   603.8  765.35   681.5  777.38   700.9     780   730.1  782.78   759.2  783.56
#Mann= 3 , 0 , 0
       0      .1       0   423.3    .045       0   443.3      .1       0
Bank Sta=423.3,443.3
XS Rating Curve= 0 ,0
Exp/Cntr=0.3,0.1

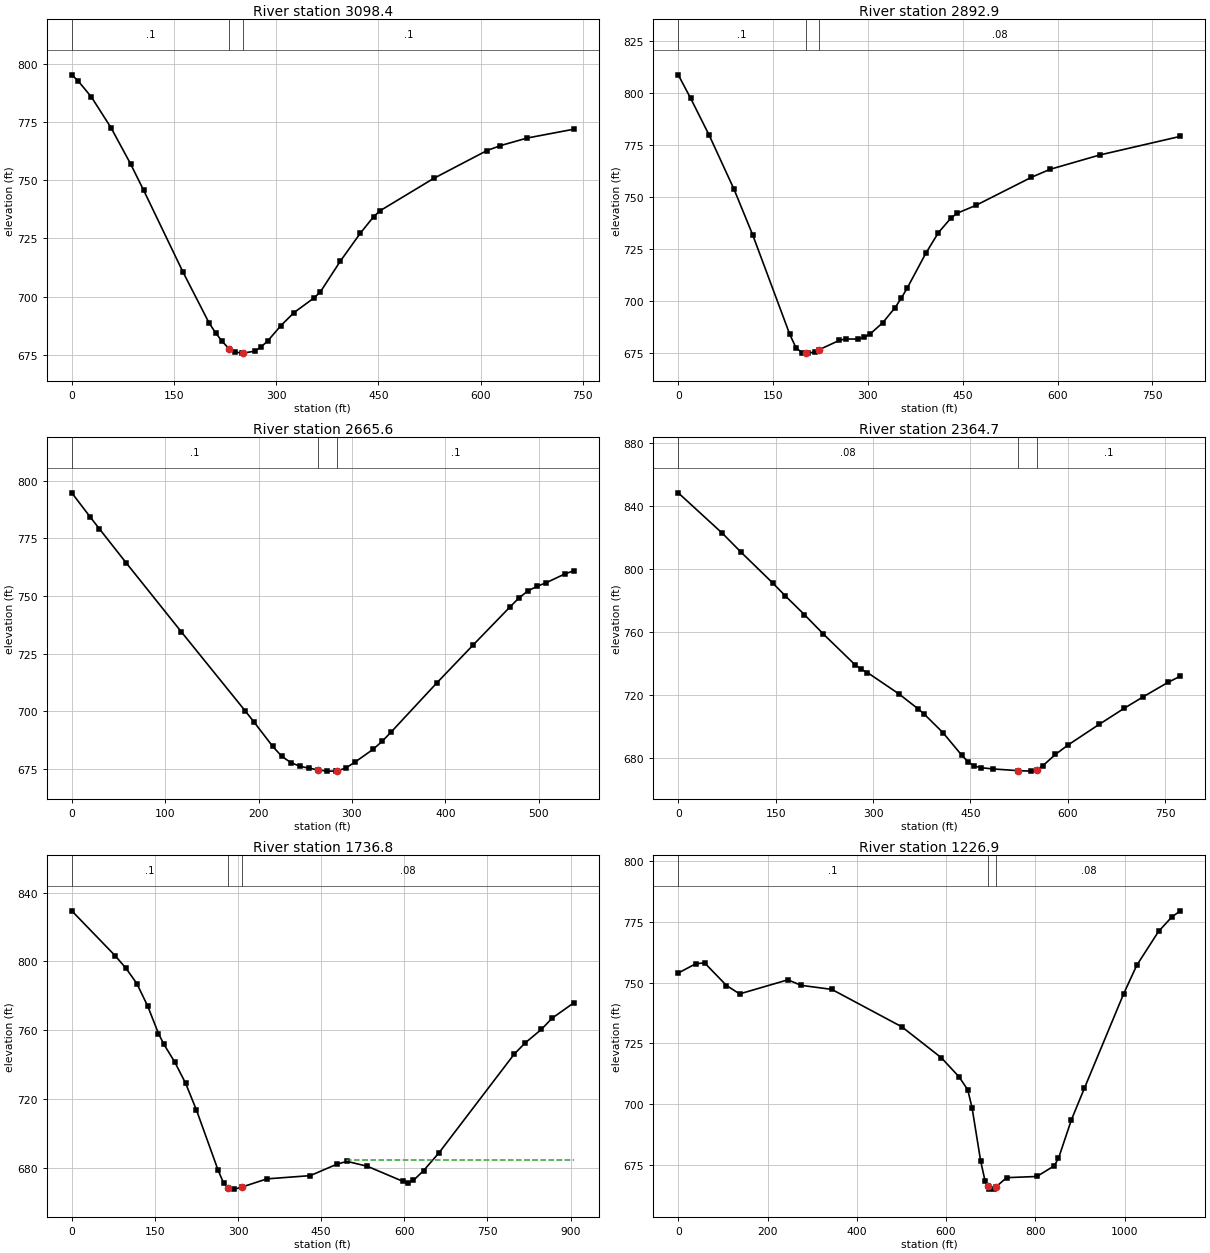
Type RM Length L Ch R = 1 ,3098.4  ,231.2,205.5,179.9
XS GIS Cut Line= 3
     1896721.808      565602.891     1896434.897      565378.014
     1896062.688      565376.464
#Sta/Elev= 30
       0  795.19     9.6  792.48    28.8  785.68    57.6  772.49    86.3  756.98
   105.5  745.65   163.1  710.65   201.4   688.8     211  684.51   220.6  680.88
   231.3  677.52   239.8  676.26   249.4   675.8   251.3  675.83   268.6  676.63
   278.2  678.56   287.8  681.11     307  687.63   326.2  693.21   354.9  699.34
   364.5  701.93   393.9  715.16   423.3  727.19   442.9  734.31   452.7  736.93
     531  750.74   609.4  762.72     629  764.81   668.2  768.07   736.8  771.86
#Mann= 3 , 0 , 0
       0      .1       0   231.3    .045       0   251.3      .1       0
Bank Sta=231.3,251.3
XS Rating Curve= 0 ,0
Exp/Cntr=0.3,0.1

Type RM Length L Ch R = 1 ,2892.9  ,232.5,227.2,222
XS GIS Cut Line= 3
     1896747.074      565195.981     1896329.373      565365.543
     1895986.114      565363.475
#Sta/Elev= 30
       0  808.62    19.6  797.38      49  779.59    88.2  753.72   117.6  731.94
   176.4  684.05   186.2  677.66     196  675.18     202   675.1   205.8  675.05
   215.6  675.58     222  676.57   254.8  681.18   264.6  681.84   284.2  681.78
     294  682.57   303.8  684.33   323.4  689.63     343   696.9   352.8  701.43
   362.6  706.53     392   723.2   411.6  732.93   431.2  739.82     441  742.18
   470.4  745.91   558.7  759.45   588.1  763.27   666.6  770.14   794.1  779.08
#Mann= 3 , 0 , 0
       0      .1       0     202    .045       0     222     .08       0
Bank Sta=202,222
XS Rating Curve= 0 ,0
Exp/Cntr=0.3,0.1

Type RM Length L Ch R = 1 ,2665.6  ,298,300.9,303.8
XS GIS Cut Line= 2
     1896634.959      564948.423     1896188.308      565247.741
#Sta/Elev= 30
       0  794.74    19.6  784.32    29.3  779.26    58.6  764.19   117.3  734.45
   185.7  700.15   195.5  695.13   215.1  684.79   224.8  680.46   234.6  677.71
   244.4   676.1   254.2  675.26   264.2  674.51   273.7     674   283.5     674
   284.2  674.09   293.3  675.31     303  677.83   322.6  683.42   332.4  686.93
   342.2  691.03     391   712.3   430.1  728.83   469.2  745.18     479  749.17
   488.8  752.28   498.6  754.22   508.3  755.77   527.9  759.52   537.7  760.93
#Mann= 3 , 0 , 0
       0      .1       0   264.2    .045       0   284.2      .1       0
Bank Sta=264.2,284.2
XS Rating Curve= 0 ,0
Exp/Cntr=0.3,0.1

Type RM Length L Ch R = 1 ,2364.7  ,604.5,627,648.2
XS GIS Cut Line= 3
     1896734.667      564889.943     1896335.576      564805.162
     1896010.927      564972.656
#Sta/Elev= 30
       0  848.44      68  822.75    97.1  810.61   145.7  791.15   165.1  782.96
   194.3  771.15   223.4  758.87     272  739.45   281.7  736.51   291.4  734.37
     340   720.8   369.1  711.44   378.8  708.03     408  696.12   436.8  681.84
   446.4  677.72   456.1  675.06   465.7  674.02   484.9  673.19   523.7  672.13
   542.6  671.82   552.2  672.57   561.8  675.32     581  682.44   600.3  688.38
   648.3  701.49   686.8  711.67   715.6  718.86   754.1   728.1   773.3  732.08
#Mann= 3 , 0 , 0
       0     .08       0   523.7    .045       0   552.2      .1       0
Bank Sta=523.7,552.2
XS Rating Curve= 0 ,0
Exp/Cntr=0.3,0.1

Type RM Length L Ch R = 1 ,1736.8  ,553.9,509.9,467.2
XS GIS Cut Line= 5
     1896794.634      564753.466     1896383.718      564570.011
     1896287.564      564535.892     1896168.082      564542.548
     1895948.893      564625.261
#Sta/Elev= 30
       0  829.38    78.3   803.3    97.8  796.03   117.4  787.13     137  774.05
   156.5   758.1   166.3  751.81   185.9  741.49   205.4  729.22     225  713.65
   264.1  678.68   273.9  671.28  281.46  668.66   293.5  667.72   306.5  668.88
   352.2  673.68   430.4  675.56   477.8  682.12   496.4  683.85   533.5  680.98
   598.1  672.16   607.3  671.57   616.5  672.79   634.9   678.5   662.5  688.75
   798.6  746.23   818.1  752.62   847.4   760.5   866.9  767.04     906  775.96
#Mann= 3 , 0 , 0
       0      .1       0  281.46    .045       0   306.5     .08       0
#XS Ineff= 2 , 0
                          496.26          684.75
Permanent Ineff=
       F       F
Bank Sta=281.46,306.5
XS Rating Curve= 0 ,0
Exp/Cntr=0.3,0.1

Type RM Length L Ch R = 1 ,1226.9  ,347.6,345.2,342.9
XS GIS Cut Line= 4
     1896840.126      564149.661     1896219.326       564300.16
     1896157.743      564534.276     1895928.214       564616.99
#Sta/Elev= 30
       0  753.91    39.3  757.75      59  758.11   108.1  748.77   137.6  745.32
   245.7  751.12   275.2  748.85     344  747.18   501.2  731.73   589.6  718.99
     629  711.18   648.5  705.84   658.2  698.49   677.5  676.49   687.2  668.41
  693.87  666.21   696.9  665.08   706.6   664.9   712.8  665.98   735.6  669.62
   803.4  670.11   842.1  674.46   851.8  677.54   880.9   693.5   910.1  706.54
     998  745.42  1027.2  757.09    1076  771.04  1105.3  776.91  1124.8  779.54
#Mann= 3 , 0 , 0
       0      .1       0  693.87    .045       0   712.8     .08       0
Bank Sta=693.87,712.8
XS Rating Curve= 0 ,0
Exp/Cntr=0.3,0.1

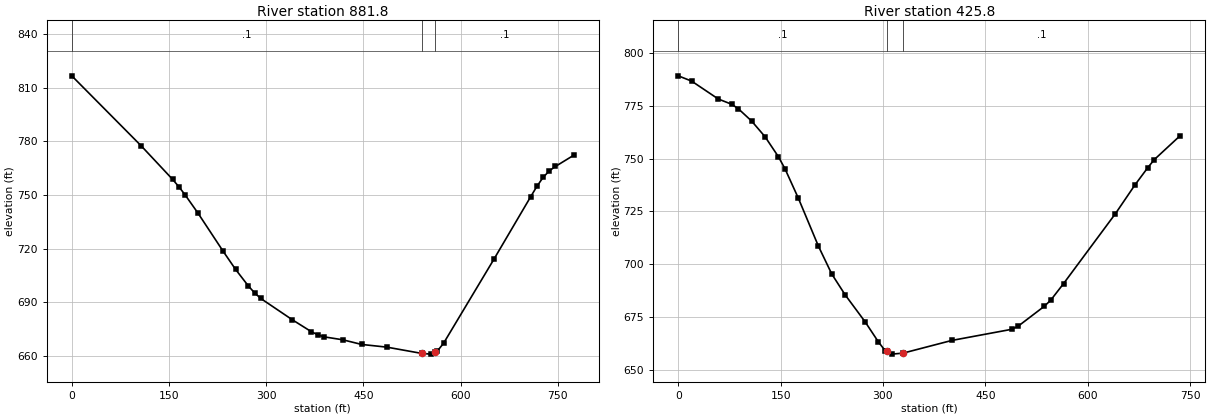
Type RM Length L Ch R = 1 ,881.8   ,459.9,455.8,451.8
XS GIS Cut Line= 3
     1895955.096      563831.215     1895847.569       564463.97
     1895835.162      564596.311
#Sta/Elev= 30
       0  816.72     107   777.6   155.6  758.79   165.3  754.65     175  750.07
   194.5  740.05   233.4  718.67   252.8  708.42   272.3  699.25     282  695.33
   291.7  692.15   340.4  680.23   369.5  673.63   379.3  671.86     389  670.71
   418.2  669.04   447.3  666.44   486.2  664.93   540.2  661.41   554.3  661.02
   560.2  662.02     564  662.66   573.8  667.13   651.3  714.02   708.3  749.15
   717.8  754.88   727.3  759.87   736.8  763.51   746.3     766   774.8  772.33
#Mann= 3 , 0 , 0
       0      .1       0   540.2    .045       0   560.2      .1       0
Bank Sta=540.2,560.2
XS Rating Curve= 0 ,0
Exp/Cntr=0.3,0.1

Type RM Length L Ch R = 1 ,425.8   ,415.2,425.8,436.5
XS GIS Cut Line= 4
     1895458.818      564013.184     1895412.873      564233.472
     1895411.258      564497.056     1895636.651      564598.379
#Sta/Elev= 30
       0  789.06    19.6  786.57    58.7  778.11    78.3  775.63      88  773.53
   107.6  767.68   127.2   760.3   146.8  750.85   156.5  745.11   176.1  731.19
   205.5  708.55     225  695.44   244.6  685.61   273.8   672.9   293.4  663.35
   303.1   659.3   305.5  658.89   312.9  657.62  329.45  658.09   400.8  664.08
   488.6  669.34   498.1  670.82   536.1  680.14   545.6  683.01   564.6  690.92
   640.7  723.99   669.2  737.52   688.2  745.76   697.7  749.53   735.7  760.86
#Mann= 3 , 0 , 0
       0      .1       0   305.5    .045       0  329.45      .1       0
Bank Sta=305.5,329.45
XS Rating Curve= 0 ,0
Exp/Cntr=0.3,0.1

Chan Stop Cuts=-1
Use User Specified Reach Order=0
Composite Channel Slope=5